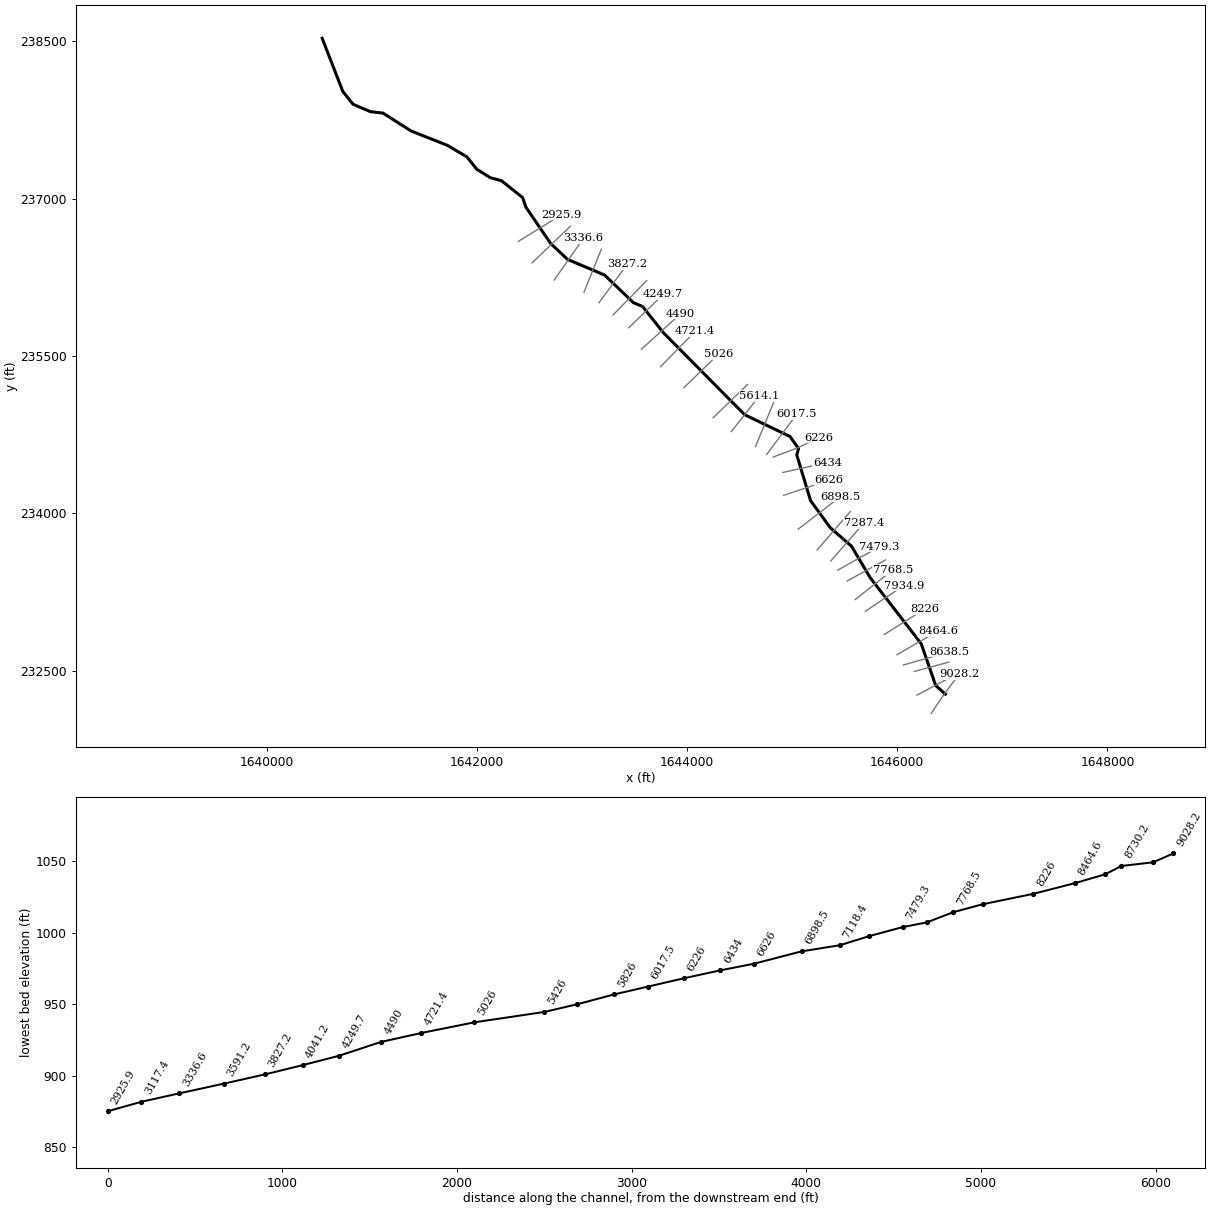
--- mtchllbrnc.prj (project) ---

Proj Title=mtchllbrnc
Current Plan=p01
Default Exp/Contr=0,0
English Units
Geom File=g01
Flow File=f01
Plan File=p01
BEGIN DESCRIPTION:
END DESCRIPTION:
DSS Export Rating Curves= 0
DSS Export Rating Curve Sorted= 0
DSS Export Volume Flow Curves= 0
DXF OffsetX= 0
DXF OffsetY= 0
DXF ScaleX= 0
DXF ScaleY= 0

--- mtchllbrnc.p01 (plan) ---

Plan Title=Approximate Study - 100yr
Program Version=4.00
Geom File=g01
Flow File=f01
Subcritical Flow
K Sum by GR= 0
Std Step Tol= 0.01
Critical Tol= 0.01
Num of Std Step Trials= 20
Max Error Tol= 0.3
Flow Tol Ratio= 0.001
Split Flow NTrial= 30
Split Flow Tol= 0.02
Split Flow Ratio= 0.02
Log Output Level= 0
Friction Slope Method= 1
Unsteady Friction Slope Method= 2
Unsteady Bridges Friction Slope Method= 1
Parabolic Critical Depth
Global Vel Dist= 0 , 0 , 0
Global Log Level= 0
CheckData=True
Encroach Param=-1 ,0,0, 0
Run HTab= 0
Run UNet= 0
Run PostProcess= 0
Run WQNet= 0
UNET Theta= 0
UNET Theta Warmup= 0
UNET ZTol= 0
UNET ZSATol= 0
UNET MxIter= 0
UNET MaxInSteps= 0
UNET DtIC= 0
UNET DtMin= 0
UNET MaxCRTS= 0
UNET WFStab= 0
UNET SFStab= 0
UNET WFX= 1
UNET SFX= 1
UNET DSS MLevel= 1
UNET DZMax Abort= 0
UNET Convert EG Bridges= 0
UNET Use Existing IB Tables= 0
UNET Froude Reduction=False
UNET Froude Limit= 0
UNET Froude Power= 0
UNET Time Slicing=0,0, 5
Write IC File= 0
Echo Input=False
Echo Output=False
Write Detailed= 0
Detailed Automatic Start=False, 0
WQ ULTIMATE=-1
WQ Max Comp Step=1HOUR
WQ Output Interval=15MIN
WQ Output Selected Increments= 0
WQ Output face flow=0
WQ Output face velocity=0
WQ Output face area=0
WQ Output face dispersion=0
WQ Output cell volume=0
WQ Output cell surface area=0
WQ Output cell continuity=0
WQ Output face conc=0
WQ Output face dconc_dx=0
WQ Output face courant=0
WQ Output face peclet=0
WQ Output face adv mass=0
WQ Output face disp mass=0
WQ Output cell mass=0
WQ Output cell source sink temp=0
WQ Output cell source sink nsm=0
WQ Output MaxMinRange=-1
WQ Daily Max Min Mean=-1
WQ Daily Range=0
WQ Daily Time=0
WQ Create Restart=0
WQ Fixed Restart=0
WQ System Summary=False
Sorting and Armoring Iterations= 10
XS Update Threshold= 0.02
Hydraulics Update Threshold= 0.02
Energy Slope Method= 1
Volume Change Method= 0
XS Weighting Method= 0
Number of US Weighted Cross Sections= 1
Number of DS Weighted Cross Sections= 1
Upstream XS Weight=0.25
Main XS Weight=0.5
Downstream XS Weight=0.25
Number of DS XS's Weighted with US Boundary= 1
Upstream Boundary Weight= 1
Weight of XSs Associated with US Boundary= 0
Number of US XS's Weighted with DS Boundary= 1
Downstream Boundary Weight= 0.5
Weight of XSs Associated with DS Boundary= 0.5
Sediment Output Level= 4
Mass or Volume Output= 0
Output Increment Type= 1
Profile and TS Output Increment= 10
XS Output Flag= 0
XS Output Increment= 10
Disregard all LS=0
Disregard all Conn=0
Disregard all Breaches=0
Disregard all Pumps=0

--- mtchllbrnc.f01 (steady flow) ---

Flow Title=USGS Regression Equation
Program Version=4.00
Number of Profiles= 1
Profile Names=P100yr
River Rch & RM=mtchllbrnc,Main            ,9028.2
     376
River Rch & RM=mtchllbrnc,Main            ,8638.5
     397
River Rch & RM=mtchllbrnc,Main            ,7118.4
     435
River Rch & RM=mtchllbrnc,Main            ,5026
     469
River Rch & RM=mtchllbrnc,Main            ,2925.9
     519
River Rch & RM=mtchllbrnc,Main            ,231.6
     577
Boundary for River Rch & Prof#=mtchllbrnc,Main            , 1
Up Type= 0
Dn Type= 3
Dn Slope=0.004999
DSS Import GetInterval= 0
DSS Import GetPeak= 0
DSS Import FillOption= 0

--- mtchllbrnc.g01 (geometry) ---

Geom Title=USGS 3m DEM
Program Version=4.00

River Reach=mtchllbrnc      ,Main
Reach XY= 30
     1646458.185      232276.486     1646366.075      232358.016
     1646227.985      232756.962     1645742.264      233387.301
      1645564.36       233687.59      1645363.25      233862.649
     1645175.334      234121.185      1645043.93      234556.989
     1645060.399      234618.387     1644979.979      234732.719
      1644548.11      234940.785     1643774.166       235723.35
     1643575.792      235973.721     1643489.234      236009.321
     1643214.575      236273.194     1642862.364      236422.146
     1642700.637      236575.321     1642465.575      236921.011
     1642434.929       237011.61     1642234.081      237172.405
     1642128.266      237200.675      1641998.63      237281.795
     1641903.968      237400.766     1641717.211      237510.481
     1641373.076      237647.023     1641106.818      237816.744
     1640986.808      237831.028     1640821.517      237901.418
     1640723.851      238024.215     1640527.947      238530.069

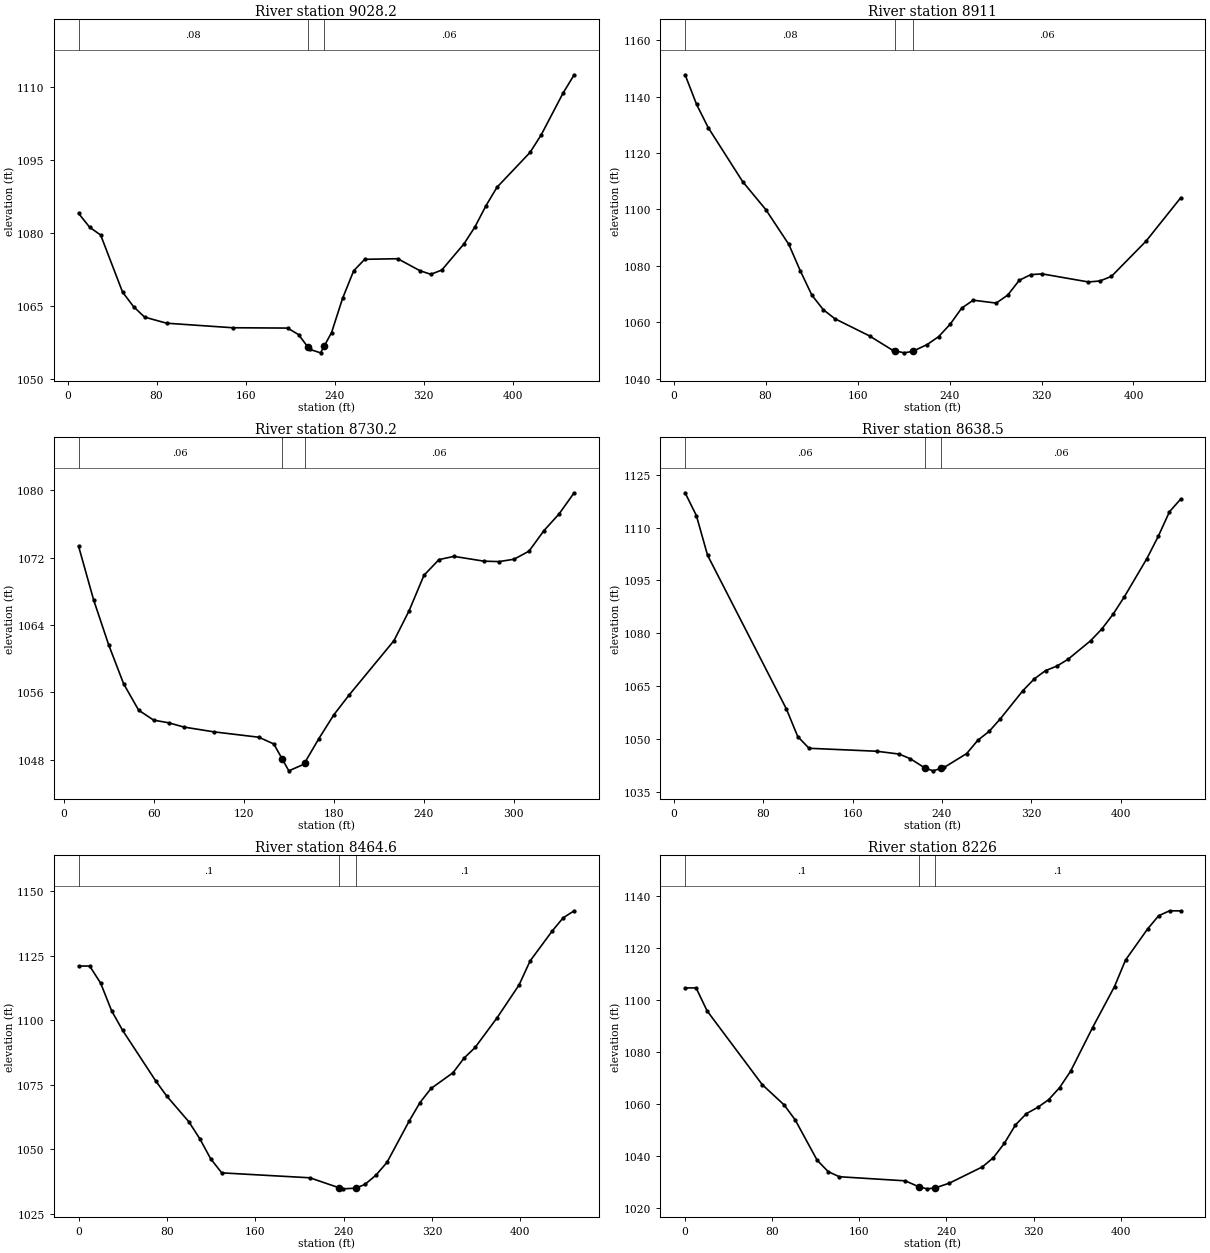
Type RM Length L Ch R = 1 ,9028.2  ,128.4,117.2,107.3
XS GIS Cut Line= 3
     1646323.478      232092.988     1646449.872      232282.044
     1646587.538      232463.768
#Sta/Elev= 30
     9.9 1084.06    19.8 1081.23    29.7 1079.63    49.4 1067.92    59.3 1064.93
    69.2 1062.79      89 1061.54   148.3 1060.61   197.8 1060.54   207.6  1059.2
   215.91056.676   217.5 1056.19   227.4 1055.46   230.91056.935   237.3 1059.63
   247.2 1066.64   257.2 1072.31   267.1 1074.65   296.8 1074.77   316.6 1072.33
   326.5 1071.57   336.4 1072.45   356.3 1077.81   366.2  1081.3   376.1 1085.64
     386 1089.43   415.7 1096.57   425.7 1100.16   445.5 1108.79   455.4 1112.51
#Mann= 3 , 0 , 0
     9.9     .08       0   215.9    .045       0   230.9     .06       0
Bank Sta=215.9,230.9
XS Rating Curve= 0 ,0
Exp/Cntr=0.3,0.1

Type RM Length L Ch R = 1 ,8911    ,185.8,180.8,175.8
XS GIS Cut Line= 2
     1646187.321      232267.103     1646576.933      232473.635
#Sta/Elev= 30
      10  1147.7      20  1137.2    30.1 1128.99    60.1 1109.84    80.2 1099.95
   100.2 1087.65   110.2 1078.28   120.3 1069.63   130.3 1064.47   140.3 1061.31
   170.4 1055.22   190.4 1050.17   192.9 1049.94   200.4 1049.23   207.9 1049.74
   220.5 1052.16   230.5 1054.96   240.5 1059.34   250.6 1065.08   260.6 1067.87
   280.6 1066.85   290.6 1069.68   300.7 1074.93   310.7 1076.94   320.7 1077.18
   360.8 1074.33   370.8 1074.68   380.8  1076.3   410.9 1088.78     441 1104.12
#Mann= 3 , 0 , 0
      10     .08       0   192.9    .045       0   207.9     .06       0
Bank Sta=192.9,207.9
XS Rating Curve= 0 ,0
Exp/Cntr=0.3,0.1

Type RM Length L Ch R = 1 ,8730.2  ,91.4,91.7,92
XS GIS Cut Line= 2
     1646162.356      232492.548     1646490.689      232581.819
#Sta/Elev= 30
      10 1073.32      20 1066.97      30 1061.65      40 1057.01      50 1053.88
      60  1052.7    70.1 1052.38    80.1 1051.88   100.1 1051.31   130.1 1050.67
   140.1 1049.87   145.61048.114   150.1 1046.68   160.1 1047.46   160.61047.612
   170.1  1050.5   180.1 1053.33   190.1 1055.64   220.2 1062.14   230.2 1065.66
   240.2  1069.9   250.2 1071.76   260.2 1072.14   280.2 1071.57   290.2 1071.52
   300.2  1071.8   310.2 1072.76   320.2 1075.21   330.2 1077.17   340.3 1079.69
#Mann= 3 , 0 , 0
      10     .06       0   145.6    .045       0   160.6     .06       0
Bank Sta=145.6,160.6
XS Rating Curve= 0 ,0
Exp/Cntr=0.3,0.1

Type RM Length L Ch R = 1 ,8638.5  ,168.2,173.9,179.6
XS GIS Cut Line= 2
     1646057.458      232554.105      1646493.51      232679.203
#Sta/Elev= 30
    10.1 1119.91    20.2 1113.43    30.2 1102.16   100.8 1058.46   110.9 1050.66
     121 1047.32   181.5 1046.48   201.6 1045.68   211.7 1044.35   224.4 1041.79
   231.9 1040.91   239.4 1041.63   241.9 1041.87   262.1 1045.82   272.2 1049.63
   282.3 1052.15   292.3 1055.72   312.5 1063.72   322.6 1067.03   332.7 1069.39
   342.8 1070.66   352.8  1072.6     373 1077.87   383.1 1081.22   393.2 1085.44
   403.2 1090.35   423.4 1101.22   433.5 1107.49   443.6 1114.52   453.6 1118.11
#Mann= 3 , 0 , 0
    10.1     .06       0   224.4    .045       0   239.4     .06       0
Bank Sta=224.4,239.4
XS Rating Curve= 0 ,0
Exp/Cntr=0.3,0.1

Type RM Length L Ch R = 1 ,8464.6  ,237.8,238.6,239.4
XS GIS Cut Line= 2
     1645997.693      232652.193     1646385.472      232877.916
#Sta/Elev= 30
       0 1121.02      10 1121.02    19.9 1114.41    29.9 1103.65    39.9 1096.05
    69.8 1076.51    79.8 1070.62    99.7 1060.74   109.7 1054.11   119.7 1046.24
   129.6 1040.88   209.4 1038.97   235.81035.105   239.3 1034.69   250.81034.946
   259.2 1036.38   269.2 1039.98   279.2 1044.94   299.1 1060.79   309.1 1068.13
   319.1 1073.58     339 1079.68     349 1085.35     359 1089.46   378.9 1100.97
   398.8 1113.69   408.8 1122.99   428.7 1134.53   438.7 1139.69   448.7 1142.43
#Mann= 3 , 0 , 0
       0      .1       0   235.8    .045       0   250.8      .1       0
Bank Sta=235.8,250.8
XS Rating Curve= 0 ,0
Exp/Cntr=0.3,0.1

Type RM Length L Ch R = 1 ,8226    ,290.5,291.1,291.7
XS GIS Cut Line= 2
     1645875.955      232845.171      1646260.91       233087.73
#Sta/Elev= 30
       0 1104.57    10.1 1104.57    20.2 1095.73    70.8 1067.35      91  1059.5
   101.1 1053.75   121.3  1038.2   131.4 1033.85   141.6 1031.88   202.2  1030.3
   214.9 1027.96   222.4 1027.22   229.9 1027.61   242.7 1029.42     273 1035.68
   283.1 1039.23   293.2 1044.79   303.3  1051.8   313.4 1056.18   323.6 1058.54
   333.7  1061.5   343.8 1066.15   353.9 1072.45   374.1 1089.26   394.3 1105.11
   404.4 1115.29   424.7 1127.28   434.8 1132.35   444.9 1134.26     455 1134.21
#Mann= 3 , 0 , 0
       0      .1       0   214.9    .045       0   229.9      .1       0
Bank Sta=214.9,229.9
XS Rating Curve= 0 ,0
Exp/Cntr=0.3,0.1

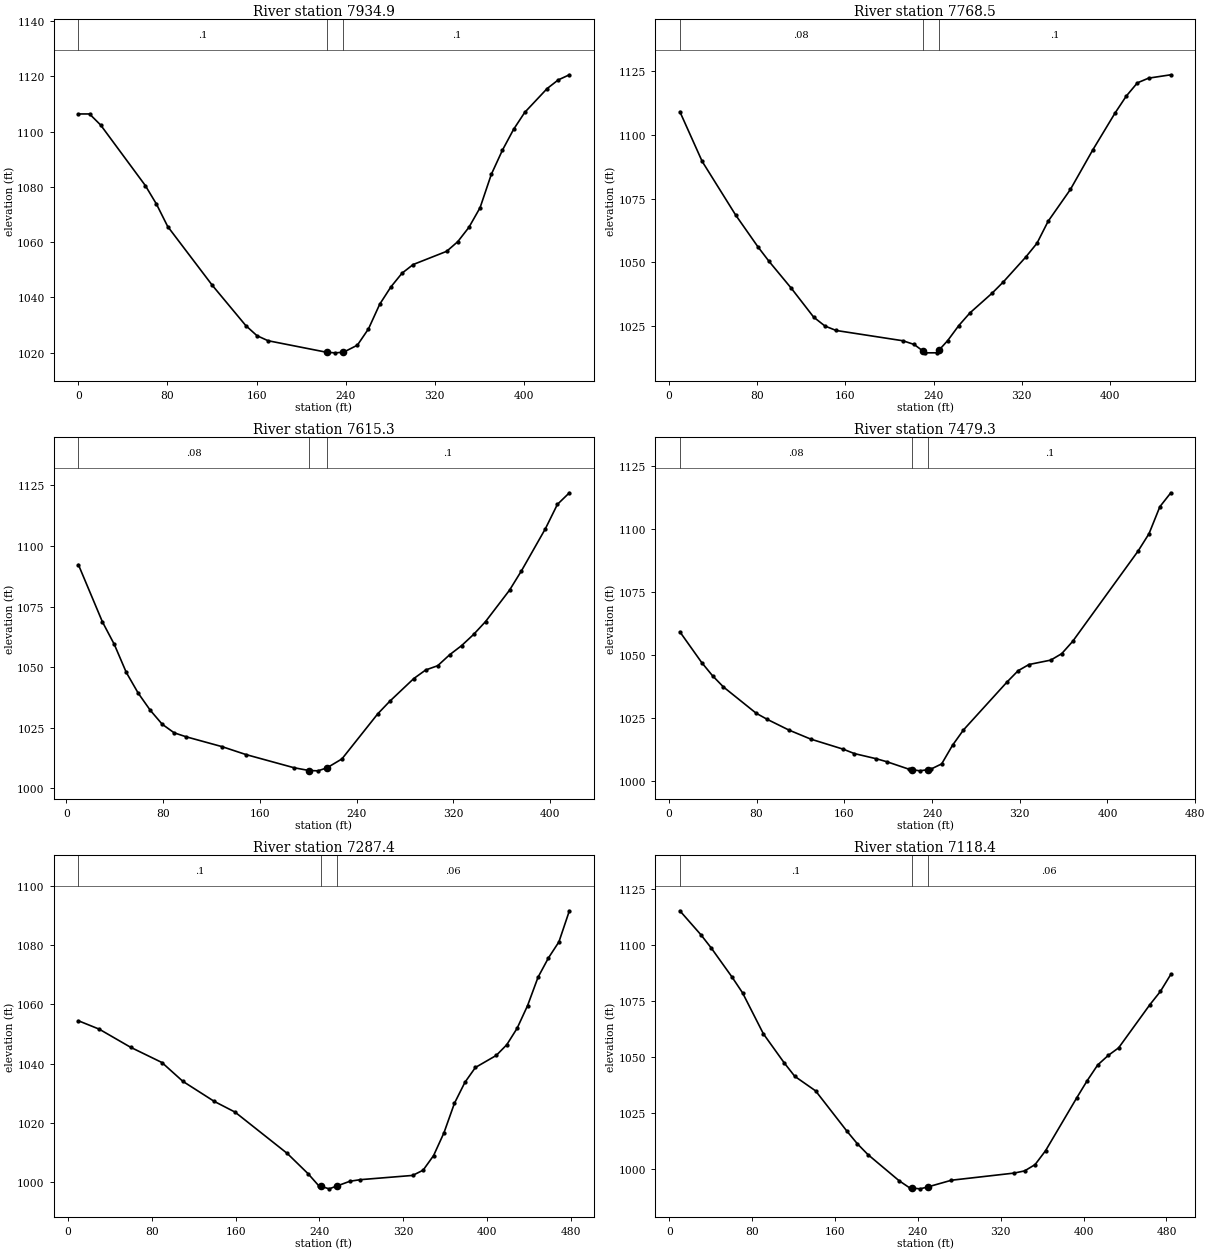
Type RM Length L Ch R = 1 ,7934.9  ,164.6,166.3,168.1
XS GIS Cut Line= 2
      1645696.73      233066.982     1646063.288      233311.997
#Sta/Elev= 30
       0 1106.43      10 1106.43      20 1102.41    60.1  1080.5    70.1 1073.78
    80.2 1065.66   120.2 1044.39   150.3 1029.79   160.3 1026.14   170.3  1024.3
     223 1020.11   230.5 1019.91     238 1020.12   250.5 1022.68   260.5  1028.6
   270.6 1037.53   280.6 1043.78   290.6 1048.75   300.6 1051.89   330.7 1056.68
   340.7 1060.19   350.7 1065.38   360.7 1072.48   370.8 1084.56   380.8 1093.33
   390.8 1100.85   400.8 1106.99   420.9 1115.62   430.9 1118.76   440.9 1120.62
#Mann= 3 , 0 , 0
       0      .1       0     223    .045       0     238      .1       0
Bank Sta=223,238
XS Rating Curve= 0 ,0
Exp/Cntr=0.3,0.1

Type RM Length L Ch R = 1 ,7768.5  ,157,153.3,149.6
XS GIS Cut Line= 2
     1645599.433      233178.775     1645956.957      233460.202
#Sta/Elev= 30
    10.1 1109.18    30.3 1089.65    60.7 1068.54    80.9 1056.04      91 1050.32
   111.2 1039.74   131.4 1028.43   141.6 1024.95   151.7 1023.21   212.3 1019.16
   222.4 1017.71   230.11015.227   232.6 1014.42   242.7 1014.43   245.11015.571
   252.8 1019.23   262.9 1025.16     273 1030.12   293.2 1037.92   303.3 1042.31
   323.6 1052.07   333.7 1057.46   343.8  1066.1     364 1078.61   384.2 1094.08
   404.4 1108.59   414.6 1115.27   424.7 1120.49   434.8 1122.33     455 1123.66
#Mann= 3 , 0 , 0
    10.1     .08       0   230.1    .045       0   245.1      .1       0
Bank Sta=230.1,245.1
XS Rating Curve= 0 ,0
Exp/Cntr=0.3,0.1

Type RM Length L Ch R = 1 ,7615.3  ,135.8,136,136.1
XS GIS Cut Line= 2
     1645523.678      233355.831     1645888.156      233556.227
#Sta/Elev= 30
     9.9  1092.3    29.7 1068.77    39.6 1059.39    49.5 1047.85    59.4 1039.26
    69.3 1032.25    79.2 1026.47    89.1 1022.92      99 1021.29   128.7 1017.22
   148.5 1013.95   188.2 1008.52   200.5 1007.38     208 1007.24   215.5 1008.49
   227.8 1012.15   257.5  1030.8   267.4 1035.96   287.2  1045.3   297.1 1048.86
     307 1050.61   316.9 1055.14   326.8 1058.92   336.7 1063.52   346.6 1068.84
   366.4 1081.78   376.3 1089.79   396.1 1107.18     406 1117.19   415.9 1121.97
#Mann= 3 , 0 , 0
     9.9     .08       0   200.5    .045       0   215.5      .1       0
Bank Sta=200.5,215.5
XS Rating Curve= 0 ,0
Exp/Cntr=0.3,0.1

Type RM Length L Ch R = 1 ,7479.3  ,184.1,191.9,199.7
XS GIS Cut Line= 2
     1645432.423       233458.62     1645831.778      233682.413
#Sta/Elev= 30
      10 1059.23    29.9 1047.03    39.8 1041.78    49.8  1037.3    79.6 1026.89
    89.6 1024.48   109.5  1020.2   129.4 1016.61   159.2 1012.58   169.2 1010.86
   189.1 1008.82     199  1007.6   218.9 1004.67   221.4 1004.51   228.9 1004.01
   236.4  1004.5   238.8 1004.66   248.8 1006.77   258.7 1014.17   268.7 1020.26
   308.5 1039.33   318.5 1043.76   328.4 1046.23   348.3 1047.98   358.3 1050.55
   368.2 1055.38   427.9 1091.26   437.9 1098.17   447.8  1108.9   457.8 1114.43
#Mann= 3 , 0 , 0
      10     .08       0   221.4    .045       0   236.4      .1       0
Bank Sta=221.4,236.4
XS Rating Curve= 0 ,0
Exp/Cntr=0.3,0.1

Type RM Length L Ch R = 1 ,7287.4  ,168.9,169,169.1
XS GIS Cut Line= 2
     1645366.828      233545.436     1645681.296      233906.206
#Sta/Elev= 30
      10 1054.49    29.9 1051.65    59.8 1045.54    89.7 1040.39   109.7 1034.03
   139.6 1027.27   159.5 1023.64   209.4 1009.66   229.3  1002.8   239.3   998.8
   241.8  998.53   249.3  997.72   256.8  998.69   269.2 1000.29   279.2 1000.82
     329 1002.25     339 1004.02     349 1008.96   358.9 1016.65   368.9 1026.62
   378.9 1033.69   388.9 1038.71   408.8 1042.78   418.8 1046.37   428.7 1051.94
   438.7 1059.61   448.7  1069.2   458.6 1075.71   468.6 1081.12   478.6 1091.64
#Mann= 3 , 0 , 0
      10      .1       0   241.8    .045       0   256.8     .06       0
Bank Sta=241.8,256.8
XS Rating Curve= 0 ,0
Exp/Cntr=0.3,0.1

Type RM Length L Ch R = 1 ,7118.4  ,224.4,219.9,215.3
XS GIS Cut Line= 2
     1645237.569      233651.545     1645553.966      234018.102
#Sta/Elev= 30
    10.1 1115.16    30.3 1104.55    40.4  1098.6    60.5 1085.63    70.6 1078.65
    90.8 1060.33     111 1047.34   121.1 1041.41   141.2 1034.94   171.5 1016.95
   181.6 1011.33   191.7 1006.57   221.9  994.88     232  991.75   234.6  991.63
   242.1   991.3   249.6  992.16   272.4  995.14   332.9  998.32     343  999.29
   353.1 1002.09   363.2 1008.26   393.4 1031.88   403.5 1039.53   413.6 1046.49
   423.7 1050.71   433.8 1054.11     464 1073.36   474.1 1079.22   484.2 1086.84
#Mann= 3 , 0 , 0
    10.1      .1       0   234.6    .045       0   249.6     .06       0
Bank Sta=234.6,249.6
XS Rating Curve= 0 ,0
Exp/Cntr=0.3,0.1

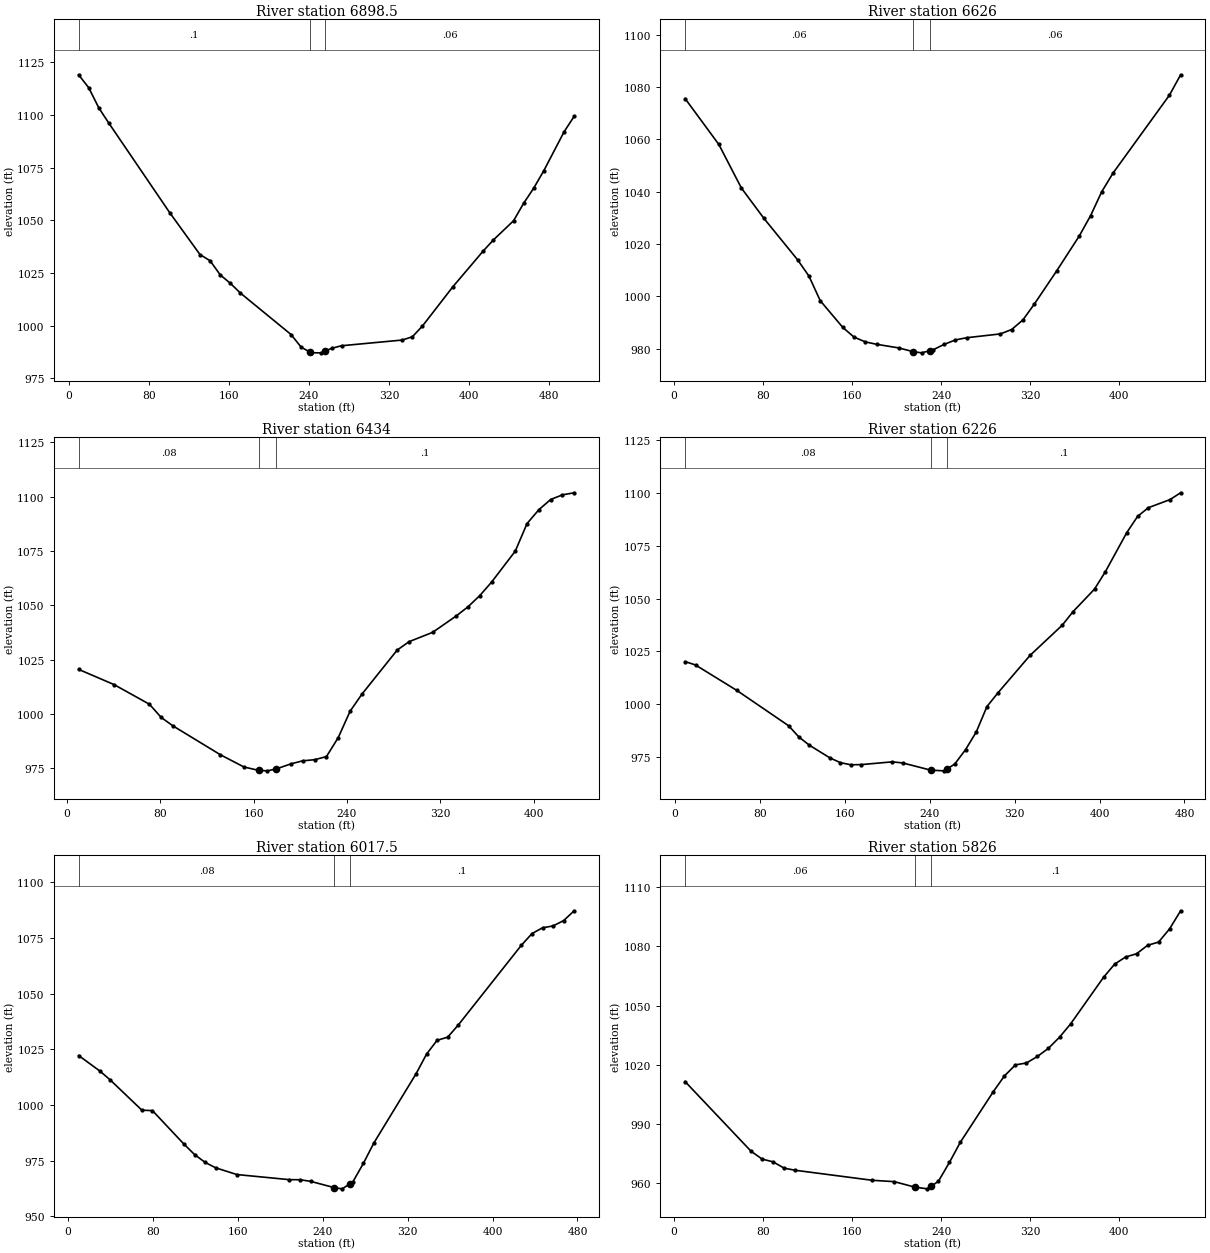
Type RM Length L Ch R = 1 ,6898.5  ,280.2,272.6,264.9
XS GIS Cut Line= 2
     1645058.148      233850.257     1645457.503      234158.938
#Sta/Elev= 30
    10.1 1119.15    20.2 1112.97    30.3 1103.36    40.4 1096.07   100.9  1053.7
   131.2 1033.73   141.3 1030.78   151.4 1024.08   161.5 1020.07   171.6  1015.4
   222.1  995.72   232.2  989.71   240.9 987.402   242.3  987.03   252.4  987.01
   255.9 987.752   262.5  989.15   272.6  990.39   333.1  993.09   343.2  994.65
   353.3  999.77   383.6  1018.4   413.9  1035.4     424 1040.62   444.2 1049.78
   454.3 1058.12   464.4 1065.33   474.5 1073.66   494.7 1092.11   504.7  1099.4
#Mann= 3 , 0 , 0
    10.1      .1       0   240.9    .045       0   255.9     .06       0
Bank Sta=240.9,255.9
XS Rating Curve= 0 ,0
Exp/Cntr=0.3,0.1

Type RM Length L Ch R = 1 ,6626    ,194.2,192,189.7
XS GIS Cut Line= 2
      1644918.73      234172.454     1645350.687      234315.416
#Sta/Elev= 30
    10.1 1075.59    40.4 1058.04    60.7 1041.34    80.9 1029.76   111.2 1013.89
   121.3 1007.71   131.4  998.32   151.7  988.07   161.8  984.37   171.9  982.55
     182  981.63   202.2  980.22   214.9   978.8   222.4  978.36   229.9  979.19
   232.6  979.49   242.7  981.59   252.8   983.3   262.9  984.14   293.2   985.6
   303.3  987.28   313.4  990.95   323.6  996.98   343.8 1009.76     364 1023.05
   374.1 1030.78   384.2    1040   394.3  1047.1   444.9 1076.87     455 1084.69
#Mann= 3 , 0 , 0
    10.1     .06       0   214.9    .045       0   229.9     .06       0
Bank Sta=214.9,229.9
XS Rating Curve= 0 ,0
Exp/Cntr=0.3,0.1

Type RM Length L Ch R = 1 ,6434    ,204.8,208,213.1
XS GIS Cut Line= 2
     1644911.526      234390.447     1645335.961      234484.981
#Sta/Elev= 30
    10.1 1020.47    40.4 1013.49    70.8 1004.42    80.9  998.33      91  994.44
   131.5   981.2   151.7  975.55   164.4  973.97   171.9  973.76   179.4  974.63
   192.1  976.98   202.2  978.38   212.4  978.89   222.5  980.34   232.6  989.06
   242.7 1001.16   252.8    1009   283.1 1029.36   293.3 1033.23   313.5 1037.53
   333.7 1045.07   343.8 1049.28   353.9 1054.45     364 1060.65   384.3 1074.91
   394.4 1087.61   404.5 1093.98   414.6 1098.68   424.7 1100.83   434.8 1101.79
#Mann= 3 , 0 , 0
    10.1     .08       0   164.4    .045       0   179.4      .1       0
Bank Sta=164.4,179.4
XS Rating Curve= 0 ,0
Exp/Cntr=0.3,0.1

Type RM Length L Ch R = 1 ,6226    ,195.6,208.4,219.4
XS GIS Cut Line= 3
     1644819.263      234537.126     1645056.318      234626.913
     1645257.379      234723.165
#Sta/Elev= 30
     9.7 1020.08    19.5 1018.47    58.5 1006.36   107.2  989.63     117  984.24
   126.7  980.42   146.2  974.35     156  972.12   165.7  971.12   175.5  971.19
   204.7   972.5   214.5     972     241 968.567   253.5  968.24     256  969.03
   263.6  971.43   273.8  978.27   283.9  986.65     294  998.75   304.2 1005.16
   334.5 1022.97   364.9 1037.34   375.1 1043.78   395.3 1054.46   405.5 1062.71
   425.7 1081.29   435.9 1088.98     446 1093.08   466.3 1096.91   476.4 1100.16
#Mann= 3 , 0 , 0
     9.7     .08       0     241    .045       0     256      .1       0
Bank Sta=241,256
XS Rating Curve= 0 ,0
Exp/Cntr=0.3,0.1

Type RM Length L Ch R = 1 ,6017.5  ,185.8,191.6,197.3
XS GIS Cut Line= 2
     1644757.186      234562.151     1645042.714      234944.142
#Sta/Elev= 30
     9.9 1022.23    29.8  1015.3    39.7 1011.25    69.5  997.68    79.5  997.47
   109.3  982.36   119.2  977.72   129.2  974.19   139.1  971.78     159  968.76
   208.6  966.46   218.6  966.43   228.5  965.71   250.8  962.88   258.3  962.34
   265.8  964.67   268.3  965.45   278.2  973.73   288.1  982.92   327.9 1014.03
   337.8 1022.87   347.7 1029.06   357.7 1030.48   367.6  1035.9   427.2  1071.8
   437.2 1077.02   447.1 1079.61     457 1080.44     467 1082.85   476.9 1087.25
#Mann= 3 , 0 , 0
     9.9     .08       0   250.8    .045       0   265.8      .1       0
Bank Sta=250.8,265.8
XS Rating Curve= 0 ,0
Exp/Cntr=0.3,0.1

Type RM Length L Ch R = 1 ,5826    ,218.1,211.9,205.7
XS GIS Cut Line= 3
     1644651.258      234637.464      1644737.53      234847.972
     1644823.801       235058.48
#Sta/Elev= 30
     9.9 1011.39    69.2     976    79.1  972.04      89  970.63    98.9  967.43
   108.8  966.37     178  961.28   197.8  960.59     216 957.841   227.5  956.94
     231 958.289   237.4  960.76   247.3  970.33   257.2  980.67   286.8 1006.32
   296.7 1014.23   306.6 1019.88   316.5 1020.83   326.4 1024.16   336.3 1028.31
   346.2 1033.91   356.1 1040.62   385.8 1064.36   395.7 1071.01   405.5 1074.63
   415.4 1076.28   425.3 1080.57   435.2 1082.22   445.1 1088.95     455 1098.11
#Mann= 3 , 0 , 0
     9.9     .06       0     216    .045       0     231      .1       0
Bank Sta=216,231
XS Rating Curve= 0 ,0
Exp/Cntr=0.3,0.1

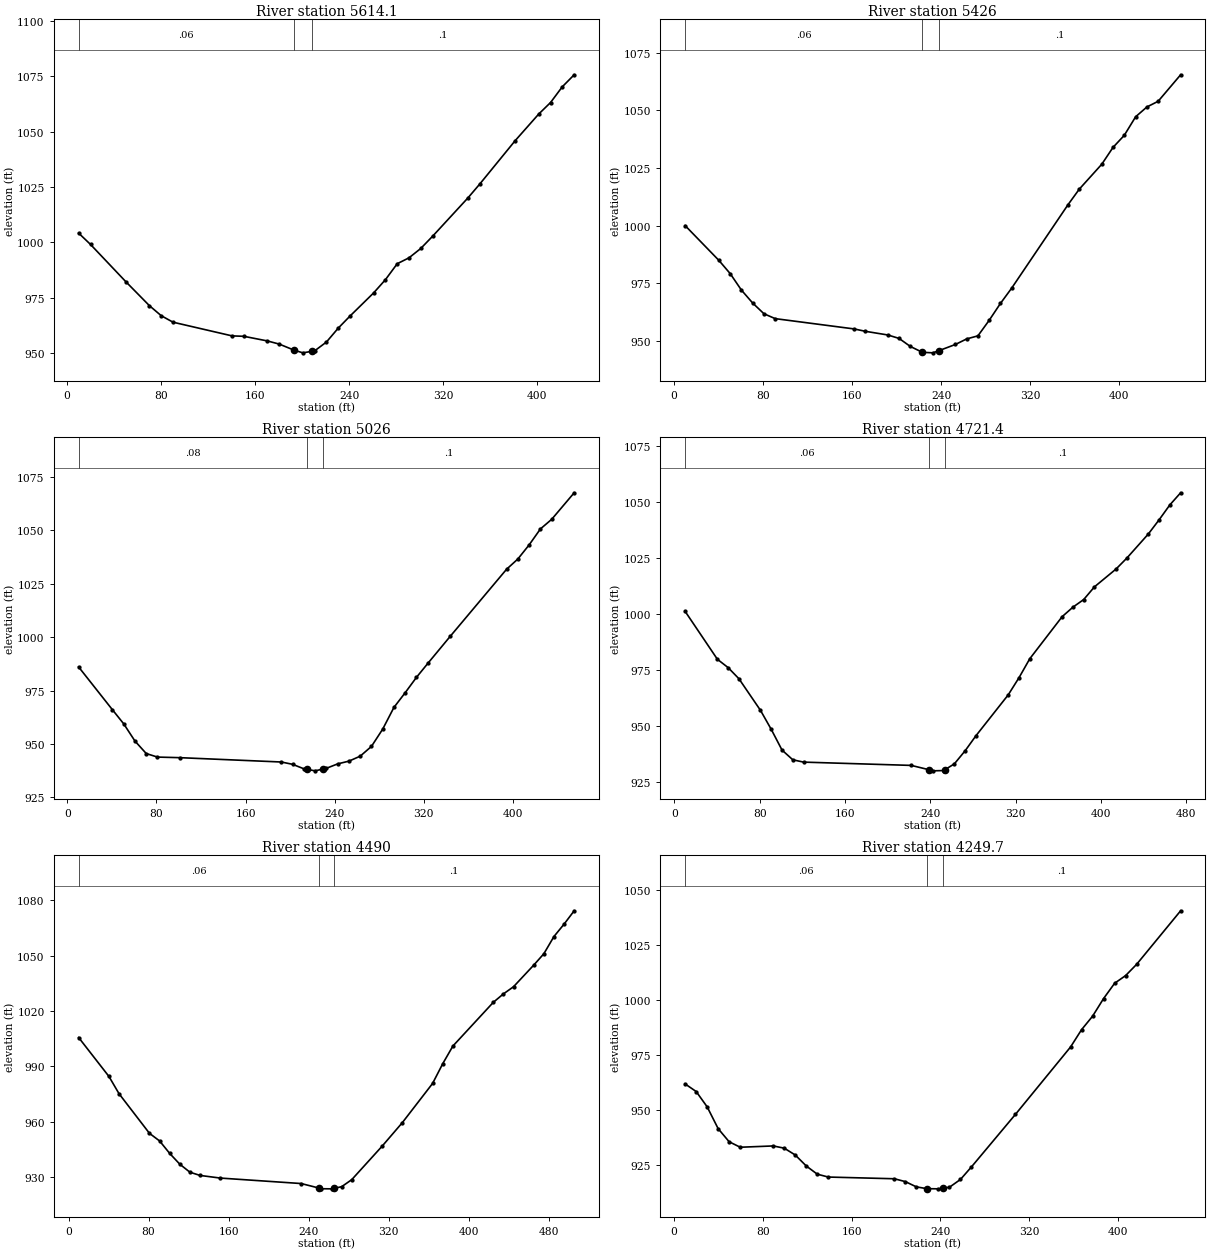
Type RM Length L Ch R = 1 ,5614.1  ,191.2,188.1,185
XS GIS Cut Line= 2
     1644421.496      234780.156     1644687.732      235119.704
#Sta/Elev= 30
      10 1004.14    20.1  999.02    50.2  982.16    70.2  971.36    80.3  966.81
    90.3  963.89   140.5  957.71   150.5  957.52   170.6  955.42   180.6  954.01
   193.2  951.28   200.7  950.05   208.2  950.71   210.7  950.93   220.8  954.94
   230.8   961.2   240.8  966.65   260.9  977.11   270.9  983.06     281  990.31
     291  992.97     301  997.19   311.1 1002.73   341.2 1020.08   351.2  1026.3
   381.3 1045.89   401.4 1057.95   411.4 1063.12   421.4 1070.24   431.5 1075.66
#Mann= 3 , 0 , 0
      10     .06       0   193.2    .045       0   208.2      .1       0
Bank Sta=193.2,208.2
XS Rating Curve= 0 ,0
Exp/Cntr=0.3,0.1

Type RM Length L Ch R = 1 ,5426    ,399.9,400,400.1
XS GIS Cut Line= 2
     1644247.902      234912.327      1644575.06      235228.543
#Sta/Elev= 30
    10.1  999.97    40.4  984.87    50.6  979.09    60.7  971.92    70.8   966.3
    80.9  961.66      91  959.54   161.8  955.07   171.9  954.04   192.1  952.44
   202.2  950.95   212.3  947.46   223.1 944.914   232.6  944.68   238.1 945.648
   252.8  948.32   262.9  950.73     273  952.06   283.1  958.81   293.2  966.13
   303.3  972.79   353.9 1009.05     364 1015.79   384.2 1026.62   394.3 1033.94
   404.4 1039.17   414.6 1047.24   424.7 1051.49   434.8 1053.96     455 1065.48
#Mann= 3 , 0 , 0
    10.1     .06       0   223.1    .045       0   238.1      .1       0
Bank Sta=223.1,238.1
XS Rating Curve= 0 ,0
Exp/Cntr=0.3,0.1

Type RM Length L Ch R = 1 ,5026    ,304,304.6,305.1
XS GIS Cut Line= 2
     1643969.845      235198.575     1644295.703       235516.13
#Sta/Elev= 30
    10.1  986.02    40.4  966.04    50.6  959.41    60.7  951.35    70.8  945.53
    80.9  943.87   101.1   943.6   192.1  941.57   202.2  940.49   212.3   938.4
   214.9  938.15   222.4  937.44   229.9  938.32   232.6  938.64   242.7   940.7
   252.8  941.98   262.9   944.3     273  948.87   283.1  956.95   293.2  967.12
   303.3  973.99   313.4  981.16   323.6  987.69   343.8  1000.4   394.3 1031.72
   404.4  1036.5   414.6 1043.14   424.7 1050.58   434.8 1055.07     455 1067.49
#Mann= 3 , 0 , 0
    10.1     .08       0   214.9    .045       0   229.9      .1       0
Bank Sta=214.9,229.9
XS Rating Curve= 0 ,0
Exp/Cntr=0.3,0.1

Type RM Length L Ch R = 1 ,4721.4  ,232.8,231.4,230.1
XS GIS Cut Line= 2
     1643746.259      235397.516      1644078.09      235737.064
#Sta/Elev= 30
    10.1 1001.29    40.4  979.84    50.5   976.1    60.6  971.14    80.8  957.01
    90.9   948.5     101  939.25   111.1  934.91   121.2  933.87   222.2   932.4
   238.9  930.46   242.4  929.97   252.5   930.1   253.9 930.515   262.6  933.09
   272.7  938.94   282.8  945.63   313.1  963.93   323.2  971.59   333.3  980.07
   363.7  998.91   373.8 1003.15   383.9 1006.56     394 1012.24   414.2 1020.19
   424.3 1025.06   444.5 1035.86   454.6  1042.2   464.7 1048.88   474.8 1054.29
#Mann= 3 , 0 , 0
    10.1     .06       0   238.9    .045       0   253.9      .1       0
Bank Sta=238.9,253.9
XS Rating Curve= 0 ,0
Exp/Cntr=0.3,0.1

Type RM Length L Ch R = 1 ,4490    ,239.5,240.3,241
XS GIS Cut Line= 2
     1643564.909       235565.36     1643939.184      235904.908
#Sta/Elev= 30
    10.1 1005.71    40.4   984.6    50.5  975.23    80.9  953.77      91  949.66
   101.1   942.9   111.2  937.05   121.3  932.72   131.4  930.97   151.6  929.54
   232.5  926.57   250.3 924.118   252.7  923.75   262.8   923.7   265.3 923.987
   272.9  924.85     283  928.66   313.3  946.77   333.5  959.52   363.8  980.81
     374  991.55   384.1 1001.08   424.5 1024.78   434.6 1029.35   444.7 1033.23
   464.9 1044.95     475  1051.1   485.1 1060.44   495.2 1067.15   505.3 1074.39
#Mann= 3 , 0 , 0
    10.1     .06       0   250.3    .045       0   265.3      .1       0
Bank Sta=250.3,265.3
XS Rating Curve= 0 ,0
Exp/Cntr=0.3,0.1

Type RM Length L Ch R = 1 ,4249.7  ,207.5,208.5,209.5
XS GIS Cut Line= 2
     1643444.548      235769.702     1643772.467      236087.639
#Sta/Elev= 30
     9.9  961.72    19.9  958.26    29.8  951.29    39.7  941.39    49.6  935.44
    59.6  932.94    89.4  933.53    99.3  932.51   109.2  929.42   119.2   924.4
   129.1  920.69     139  919.39   198.6  918.61   208.5  917.31   218.4  914.93
   227.8 914.112   238.3  914.03   242.8 914.354   248.2  914.74   258.2  918.31
   268.1  924.01   307.8  947.91   357.5  978.54   367.4   986.4   377.3   992.5
   387.2 1000.51   397.2 1007.48   407.1 1010.97     417 1016.07   456.7 1040.42
#Mann= 3 , 0 , 0
     9.9     .06       0   227.8    .045       0   242.8      .1       0
Bank Sta=227.8,242.8
XS Rating Curve= 0 ,0
Exp/Cntr=0.3,0.1

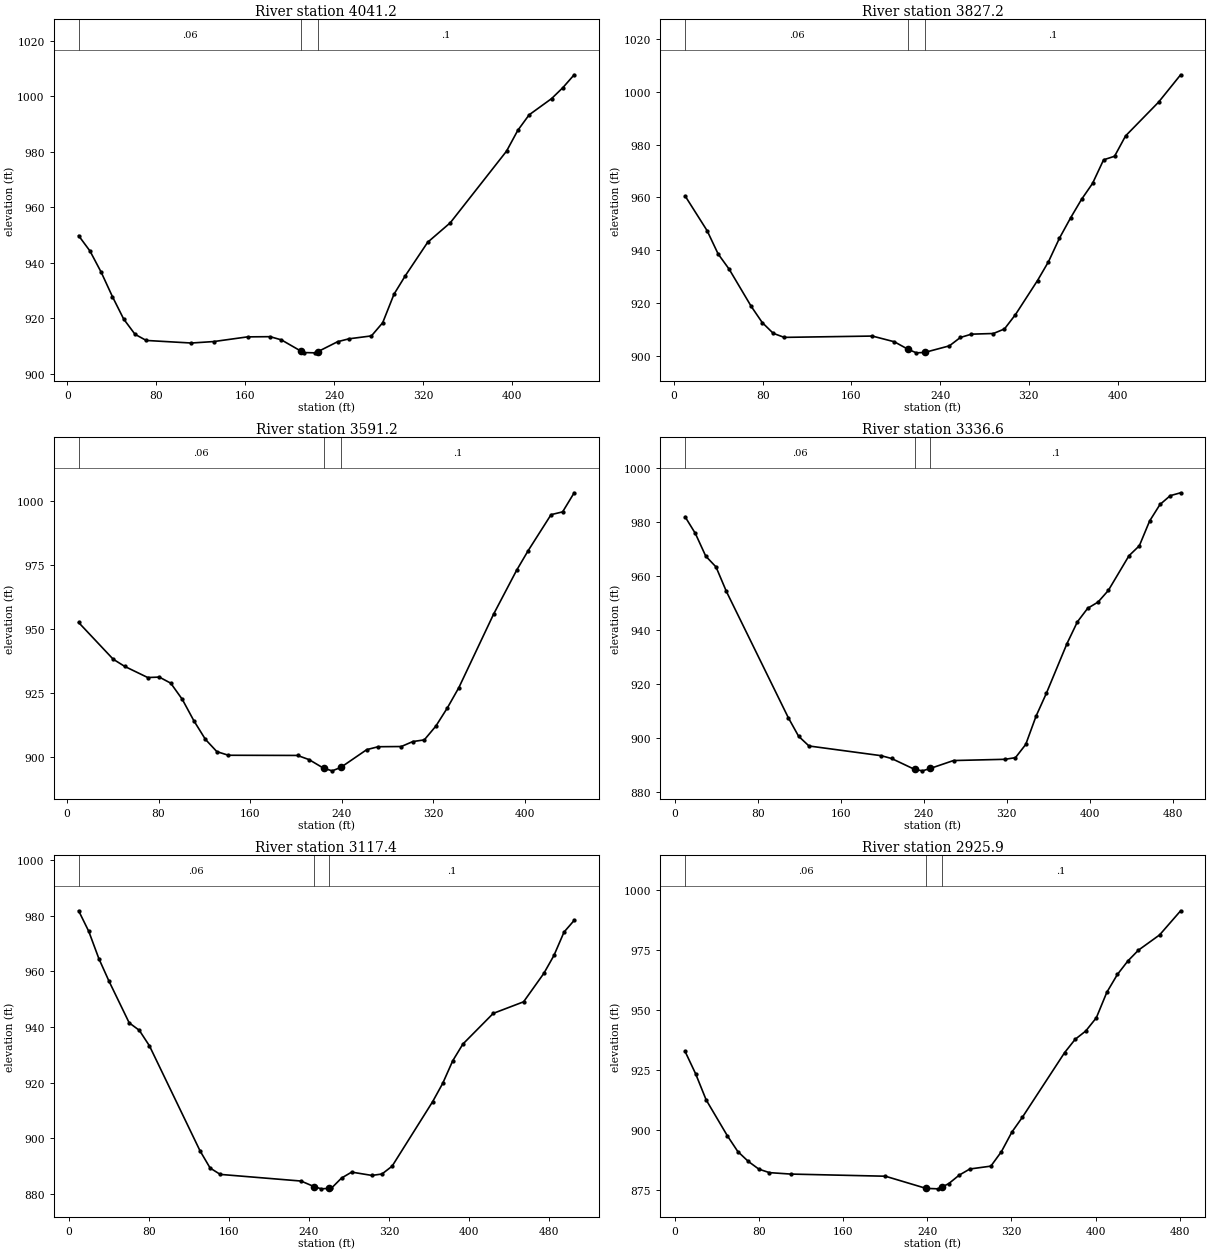
Type RM Length L Ch R = 1 ,4041.2  ,210.7,213.9,217.1
XS GIS Cut Line= 2
     1643296.744      235893.333      1643615.07      236219.376
#Sta/Elev= 30
    10.1  949.74    20.3  944.21    30.4  936.54    40.5  927.75    50.6  919.67
    60.8  914.17    70.9  911.95   111.4  911.02   131.6  911.55     162  913.24
   182.3  913.31   192.4  912.16   210.3 908.031   212.6  907.58   222.8  907.48
   225.3 907.917     243   911.5   253.2  912.54   273.4  913.59   283.5  918.33
   293.7  928.64   303.8  935.25     324  947.38   344.3  954.39   394.9  980.24
     405  987.73   415.2  993.32   435.4  999.18   445.5 1003.12   455.7 1007.77
#Mann= 3 , 0 , 0
    10.1     .06       0   210.3    .045       0   225.3      .1       0
Bank Sta=210.3,225.3
XS Rating Curve= 0 ,0
Exp/Cntr=0.3,0.1

Type RM Length L Ch R = 1 ,3827.2  ,230.4,236,241.7
XS GIS Cut Line= 2
       1643162.2      236008.961     1643431.643      236377.927
#Sta/Elev= 30
     9.9  960.56    29.8  947.35    39.7  938.56    49.7  932.75    69.5  918.72
    79.5  912.55    89.4  908.48    99.3  906.94   178.8  907.44   198.6  905.28
     211  902.43   218.5  901.08     226  901.23   248.3  903.73   258.2   906.9
   268.2  908.16     288  908.41     298  910.14   307.9  915.57   327.8  928.49
   337.7  935.63   347.6  944.55   357.6  952.21   367.5  959.25   377.4  965.27
   387.4  974.24   397.3  975.59   407.2  983.29     437   996.1   456.9 1006.47
#Mann= 3 , 0 , 0
     9.9     .06       0     211    .045       0     226      .1       0
Bank Sta=211,226
XS Rating Curve= 0 ,0
Exp/Cntr=0.3,0.1

Type RM Length L Ch R = 1 ,3591.2  ,259.7,254.6,249.4
XS GIS Cut Line= 2
     1643018.932      236109.409     1643184.847      236520.339
#Sta/Elev= 30
    10.1  952.49    40.3  938.16    50.4  935.35    70.5  931.01    80.6  931.18
    90.6  928.81   100.7  922.49   110.8  914.15   120.9  906.88   130.9  902.09
     141  900.67   201.4   900.6   211.5  898.97   224.2  895.61   231.7  894.59
   239.2  895.92   261.9  902.86   271.9     904   292.1  904.08   302.2  906.02
   312.2  906.67   322.3  912.04   332.4  919.18   342.4  927.06   372.7  955.68
   392.8  972.79   402.9  980.47     423  994.58   433.1  995.67   443.2 1003.12
#Mann= 3 , 0 , 0
    10.1     .06       0   224.2    .045       0   239.2      .1       0
Bank Sta=224.2,239.2
XS Rating Curve= 0 ,0
Exp/Cntr=0.3,0.1

Type RM Length L Ch R = 1 ,3336.6  ,223.7,219.3,214.8
XS GIS Cut Line= 2
     1642735.332      236225.164     1643015.073      236624.518
#Sta/Elev= 30
      10  982.07    19.9  975.87    29.9  967.47    39.8  963.46    49.8  954.37
   109.5  907.52   119.4  900.66   129.4  897.05     199  893.45     209  892.41
   231.3  888.35   238.8  887.83   246.3  888.72   268.7  891.65   318.4  892.11
   328.4  892.72   338.3  897.62   348.3  908.16   358.2   916.6   378.1  935.06
   388.1   943.1     398  948.12     408  950.43   417.9  954.74   437.8  967.61
   447.8  971.32   457.7   980.5   467.7  986.63   477.6   989.9   487.6  990.97
#Mann= 3 , 0 , 0
      10     .06       0   231.3    .045       0   246.3      .1       0
Bank Sta=231.3,246.3
XS Rating Curve= 0 ,0
Exp/Cntr=0.3,0.1

Type RM Length L Ch R = 1 ,3117.4  ,196.2,191.4,186.7
XS GIS Cut Line= 2
     1642525.044       236389.15     1642889.672      236738.344
#Sta/Elev= 30
    10.1  981.79    20.2  974.41    30.3   964.6    40.4  956.51    60.6  941.51
    70.7  938.83    80.8  933.26   131.3  895.54   141.4  889.34   151.5  887.06
   232.2  884.67   244.9  882.71   252.4  881.87   259.9  882.04   262.5   882.1
   272.6  885.74   282.7  887.88   302.9  886.69     313   887.2   323.1  890.01
   363.5  913.15   373.6  919.75   383.7  927.93   393.8   933.9   424.1  944.92
   454.4  949.08   474.6  959.29   484.7  965.73   494.8  974.15   504.9  978.34
#Mann= 3 , 0 , 0
    10.1     .06       0   244.9    .045       0   259.9      .1       0
Bank Sta=244.9,259.9
XS Rating Curve= 0 ,0
Exp/Cntr=0.3,0.1

Type RM Length L Ch R = 1 ,2925.9  ,285.4,282.1,278.8
XS GIS Cut Line= 2
     1642393.855       236593.65     1642802.856      236846.382
#Sta/Elev= 30
      10  932.58      20  923.28      30  912.39    50.1  897.46    60.1  890.84
    70.1  886.72    80.1  883.51    90.1  882.06   110.2  881.46   200.3  880.56
   238.9 875.493   250.4   875.3   253.9 876.051   260.4  877.45   270.4  881.01
   280.5  883.57   300.5  884.77   310.5  890.79   320.5  898.99   330.5  905.19
   370.6  932.12   380.6  937.65   390.6  941.09   400.7  946.62   410.7  957.27
   420.7  964.68   430.7  970.33   440.7  974.82   460.8  981.17   480.8  991.24
#Mann= 3 , 0 , 0
      10     .06       0   238.9    .045       0   253.9      .1       0
Bank Sta=238.9,253.9
XS Rating Curve= 0 ,0
Exp/Cntr=0.3,0.1