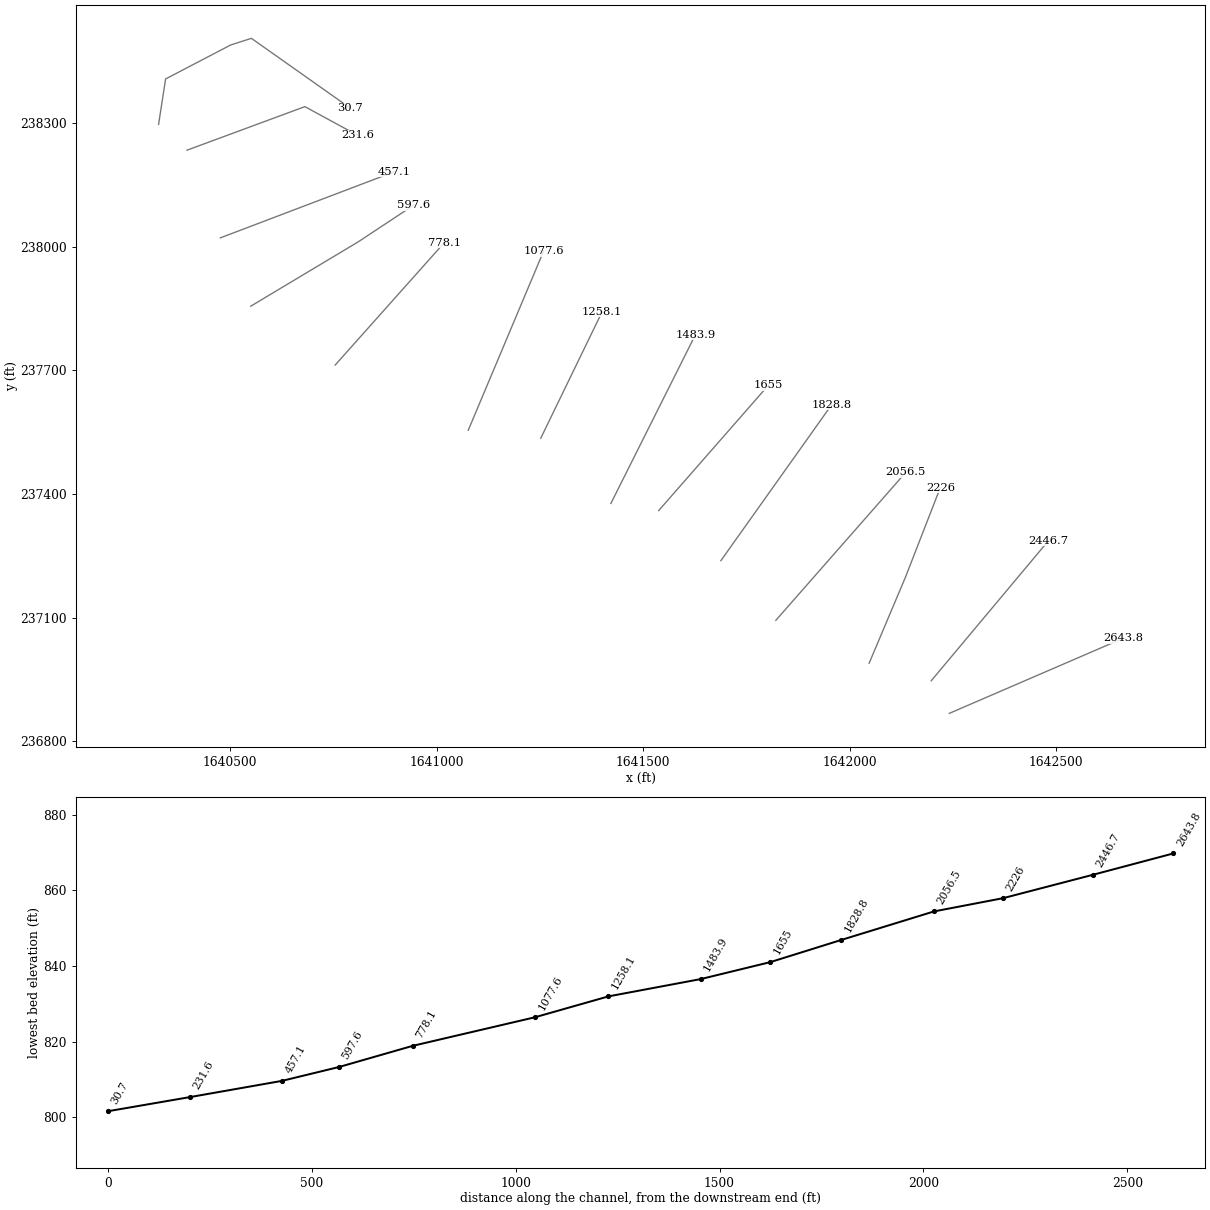
HEC-RAS study mtchllbrnc.prj: mtchllbrnc

--- mtchllbrnc.g01 (geometry) --- (continued)

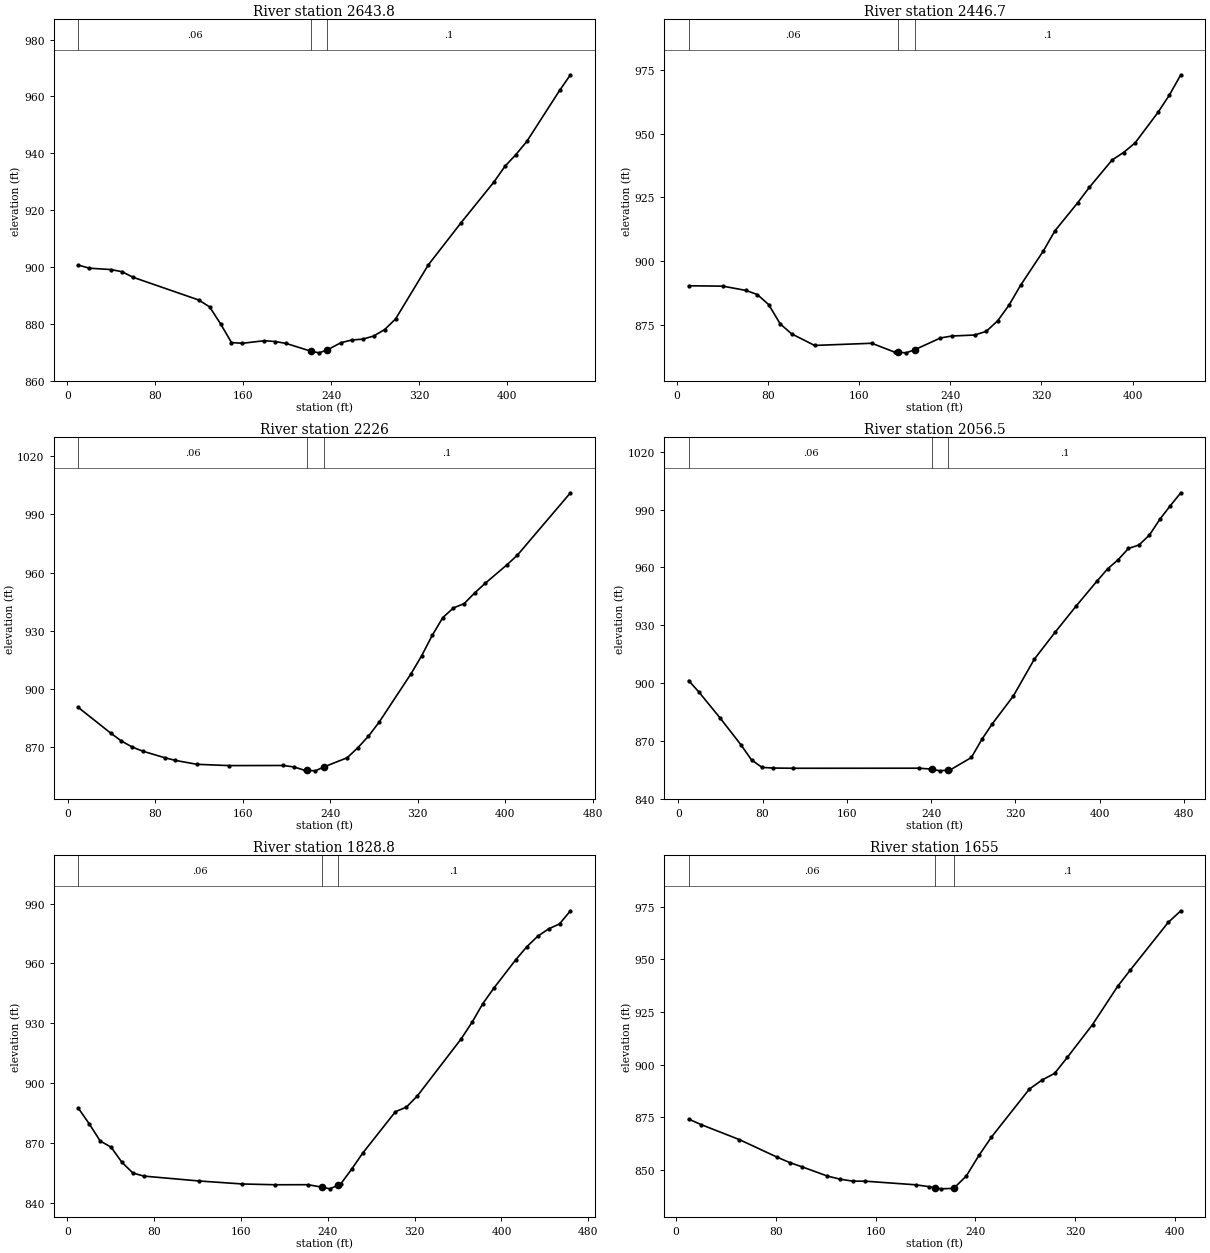
Type RM Length L Ch R = 1 ,2643.8  ,186.4,197.1,207.8
XS GIS Cut Line= 2
     1642240.827      236867.576     1642660.734      237049.307
#Sta/Elev= 30
     9.9  900.64    19.9  899.55    39.8  899.06    49.7   898.3    59.7  896.35
   119.4  888.35   129.3  885.92   139.3  879.94   149.2  873.37   159.1  873.11
     179  874.02     189  873.73   198.9  873.06   221.3  870.34   228.8  869.75
   236.3  870.77   248.7  873.32   258.6  874.27   268.6  874.57   278.5  875.66
   288.5  877.95   298.4  881.67   328.2  900.71   358.1  915.61   387.9   929.9
   397.9  935.41   407.8  939.51   417.8  944.19   447.6  962.12   457.5  967.64
#Mann= 3 , 0 , 0
     9.9     .06       0   221.3    .045       0   236.3      .1       0
Bank Sta=221.3,236.3
XS Rating Curve= 0 ,0
Exp/Cntr=0.3,0.1

Type RM Length L Ch R = 1 ,2446.7  ,214,220.7,228.1
XS GIS Cut Line= 2
     1642197.071      236946.703     1642480.671      237286.251
#Sta/Elev= 30
    10.1  890.38    40.2  890.23    60.3  888.56    70.4  886.95    80.4  882.99
    90.5  875.46   100.5  871.56   120.7  867.01   170.9  867.86     191   864.4
   193.6  864.33   201.1  864.11   208.6  865.31   231.3  869.94   241.3   870.7
   261.4  871.09   271.5  872.54   281.5  876.63   291.6  882.87   301.6  890.54
   321.7  904.04   331.8  911.89   351.9  922.94     362   928.9   382.1  939.66
   392.1  942.57   402.2  946.31   422.3  958.26   432.3  965.03   442.4  973.02
#Mann= 3 , 0 , 0
    10.1     .06       0   193.6    .045       0   208.6      .1       0
Bank Sta=193.6,208.6
XS Rating Curve= 0 ,0
Exp/Cntr=0.3,0.1

Type RM Length L Ch R = 1 ,2226    ,176.7,169.4,161.5
XS GIS Cut Line= 3
     1642046.742      236989.267      1642134.67      237197.977
     1642219.096      237415.469
#Sta/Elev= 30
     9.8  890.57    39.4  877.35    49.2  873.28    59.1  870.17    68.9  868.02
    88.6  864.71    98.5   863.3   118.2  861.29   147.7  860.62   196.9  860.68
   206.8  859.94   216.6  858.23     219  858.16   226.5  857.92     234  859.85
   255.6  864.66   265.4  869.83   275.1  875.79   284.8  882.97     314  907.93
   323.7  917.18   333.4  927.74   343.1  936.89   352.8  941.87   362.6  944.07
   372.3  949.64     382  954.62   401.5  963.98   411.2  969.01   459.8 1001.19
#Mann= 3 , 0 , 0
     9.8     .06       0     219    .045       0     234      .1       0
Bank Sta=219,234
XS Rating Curve= 0 ,0
Exp/Cntr=0.3,0.1

Type RM Length L Ch R = 1 ,2056.5  ,225.5,227.7,229.9
XS GIS Cut Line= 2
     1641820.867      237093.326     1642135.335      237452.167
#Sta/Elev= 30
     9.9  901.25    19.9  895.13    39.8   881.8    59.6  867.86    69.6  860.06
    79.5  856.22    89.5  855.88   109.3  855.76   228.6  855.79   238.6   855.4
     241  855.16   248.5  854.42     256  854.83   258.4  854.96   278.3  861.36
   288.3  870.81   298.2  878.85   318.1  893.24     338  912.32   357.9  926.42
   377.7   939.9   397.6  952.91   407.6   959.2   417.5  963.91   427.4   969.8
   437.4   971.6   447.3  976.75   457.3  985.01   467.2  992.03   477.1  998.69
#Mann= 3 , 0 , 0
     9.9     .06       0     241    .045       0     256      .1       0
Bank Sta=241,256
XS Rating Curve= 0 ,0
Exp/Cntr=0.3,0.1

Type RM Length L Ch R = 1 ,1828.8  ,176.2,173.8,171.4
XS GIS Cut Line= 2
     1641687.749       237238.02     1641955.915      237616.153
#Sta/Elev= 30
    10.1  887.32    20.2  879.43    30.2   870.9    40.3  867.76    50.4  860.09
    60.5  854.76    70.5  853.26   120.9  850.83   161.2  849.31   191.5  848.92
   221.7  848.95   234.4  847.73   241.9  846.87   249.4  848.73   251.9  849.35
     262  856.78   272.1  864.75   302.3  885.57   312.4  887.86   322.5  893.48
   362.8  922.05   372.9  930.42   382.9  939.83     393  947.56   413.2  961.82
   423.3  968.26   433.3  973.54   443.4  977.26   453.5  979.78   463.6  986.36
#Mann= 3 , 0 , 0
    10.1     .06       0   234.4    .045       0   249.4      .1       0
Bank Sta=234.4,249.4
XS Rating Curve= 0 ,0
Exp/Cntr=0.3,0.1

Type RM Length L Ch R = 1 ,1655    ,165.3,171.1,177
XS GIS Cut Line= 2
     1641537.268      237359.563     1641803.504      237664.384
#Sta/Elev= 28
    10.1  874.18    20.2  871.52    50.6  864.45    80.9  856.11    91.1   853.5
   101.2  851.44   121.4  847.08   131.5  845.62   141.7  844.68   151.8  844.65
   192.2  842.94   202.4  842.08     208 841.494   212.5  841.02   222.6  841.25
     223 841.482   232.7  847.11   242.8  856.87   252.9  865.64   283.3  888.44
   293.4  892.71   303.5  895.88   313.7  903.49   333.9  919.05   354.1  937.29
   364.2  944.99   394.6  967.63   404.7  973.15
#Mann= 3 , 0 , 0
    10.1     .06       0     208    .045       0     223      .1       0
Bank Sta=208,223
XS Rating Curve= 0 ,0
Exp/Cntr=0.3,0.1

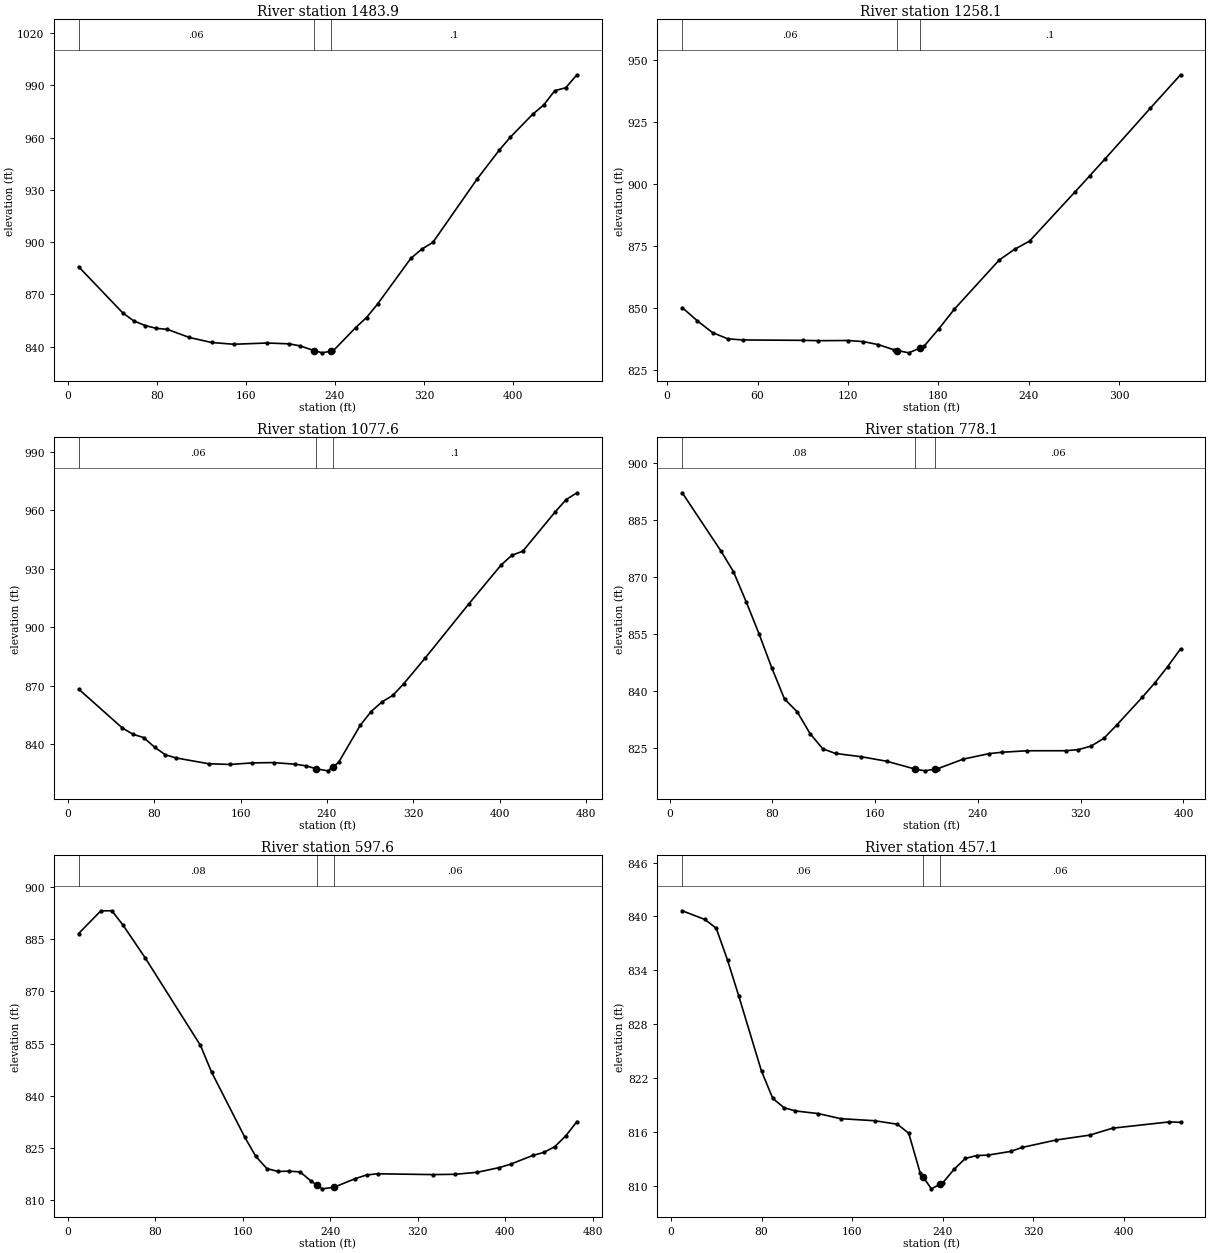
Type RM Length L Ch R = 1 ,1483.9  ,225.5,225.8,226.1
XS GIS Cut Line= 2
     1641421.513      237376.926     1641626.013      237785.927
#Sta/Elev= 30
     9.9  885.91    49.7  859.31    59.6  854.79    69.6  852.19    79.5   850.6
    89.5     850   109.3  845.34   129.2  842.48   149.1  841.45   178.9  842.16
   198.8   841.7   208.8  840.52   221.1  837.85   228.6  836.53   236.1  837.47
   238.6  837.78   258.5  850.93   268.4  856.76   278.3  864.51   308.2  890.73
   318.1  896.06     328  899.89   367.8  936.33   387.7  952.86   397.6  960.27
   417.5  973.31   427.5  978.67   437.4  986.87   447.3  988.58   457.3     996
#Mann= 3 , 0 , 0
     9.9     .06       0   221.1    .045       0   236.1      .1       0
Bank Sta=221.1,236.1
XS Rating Curve= 0 ,0
Exp/Cntr=0.3,0.1

Type RM Length L Ch R = 1 ,1258.1  ,179.4,180.6,181.7
XS GIS Cut Line= 2
     1641251.739      237535.124     1641400.291      237841.875
#Sta/Elev= 25
      10  850.21      20  844.89    30.1  840.14    40.1  837.64    50.1  837.16
    90.2  837.01   100.2  836.87   120.3  836.94   130.3   836.5   140.3  835.26
   150.4  833.23   152.9  832.91   160.4  831.97   167.9  833.91   170.4  834.55
   180.4  841.67   190.5  849.46   220.5  869.43   230.6  873.68   240.6  877.02
   270.7   896.8   280.7  903.44   290.7  910.14   320.8  930.61   340.8  944.06
#Mann= 3 , 0 , 0
      10     .06       0   152.9    .045       0   167.9      .1       0
Bank Sta=152.9,167.9
XS Rating Curve= 0 ,0
Exp/Cntr=0.3,0.1

Type RM Length L Ch R = 1 ,1077.6  ,307,299.4,291.8
XS GIS Cut Line= 2
     1641076.177      237554.417     1641258.674      237989.186
#Sta/Elev= 30
      10  868.35    50.2  848.53    60.2   845.2    70.2  843.49    80.3  838.59
    90.3  834.67   100.3  833.05   130.4  830.08   150.5  829.71   170.5   830.5
   190.6  830.67   210.7  829.82   220.7  828.98   230.3 827.463   240.8  826.44
   245.3 828.396   250.8  830.78   270.9  849.85   280.9  856.85   290.9  861.74
     301  865.11     311  871.03   331.1  884.35   371.2  911.89   401.3  931.97
   411.3  936.95   421.4  939.04   451.5  959.26   461.5  965.46   471.5  968.97
#Mann= 3 , 0 , 0
      10     .06       0   230.3    .045       0   245.3      .1       0
Bank Sta=230.3,245.3
XS Rating Curve= 0 ,0
Exp/Cntr=0.3,0.1

Type RM Length L Ch R = 1 ,778.1   ,187.1,180.6,174
XS GIS Cut Line= 2
     1640753.993      237712.615       1641018.3       238009.72
#Sta/Elev= 30
     9.9  892.15    39.8  876.93    49.7  871.41    59.6   863.5    69.6  855.06
    79.5  846.11    89.5  837.82    99.4  834.45   109.4  828.71   119.3  824.69
   129.2  823.48   149.1  822.62     169  821.43   191.3  819.35   198.8   818.9
   206.3  819.34   208.8  819.48   228.7  821.99   248.5  823.42   258.5  823.79
   278.4  824.19   308.2   824.2   318.1  824.48   328.1  825.42     338  827.46
   347.9   830.9   367.8  838.23   377.8  842.09   387.7  846.36   397.7  851.02
#Mann= 3 , 0 , 0
     9.9     .08       0   191.3    .045       0   206.3     .06       0
Bank Sta=191.3,206.3
XS Rating Curve= 0 ,0
Exp/Cntr=0.3,0.1

Type RM Length L Ch R = 1 ,597.6   ,144.5,140.5,136.5
XS GIS Cut Line= 3
     1640549.492       237855.38     1640809.941      238011.649
      1640944.99      238101.125
#Sta/Elev= 30
    10.1  886.65    30.4  893.17    40.5  893.18    50.6  889.09    70.9  879.68
   121.5   854.5   131.6  846.86     162  828.15   172.1  822.62   182.2  819.14
   192.4   818.3   202.5  818.39   212.6  818.17   222.7  815.52   228.4 814.282
   232.9  813.31   243.4 813.737   263.2  816.26   273.4  817.29   283.5  817.64
   334.1   817.4   354.4  817.49   374.6  818.06   394.9  819.43     405  820.39
   425.2  822.89   435.4  823.77   445.5  825.43   455.6  828.55   465.7  832.63
#Mann= 3 , 0 , 0
    10.1     .08       0   228.4    .045       0   243.4     .06       0
Bank Sta=228.4,243.4
XS Rating Curve= 0 ,0
Exp/Cntr=0.3,0.1

Type RM Length L Ch R = 1 ,457.1   ,225.7,225.5,225.3
XS GIS Cut Line= 2
      1640476.18      238021.295     1640896.757      238181.423
#Sta/Elev= 30
      10  840.62      30  839.65      40  838.68      50  835.12      60  831.09
      80  822.74      90   819.7     100  818.67     110  818.31     130  818.02
     150  817.45     180  817.22     200  816.83     210  815.83     220  811.45
   222.5     811     230  809.63   237.5  810.13     240  810.29     250   811.8
     260  813.02     270  813.34     280  813.39     300   813.8     310  814.24
     340  815.07     370  815.62     390  816.39     440  817.09     450  817.04
#Mann= 3 , 0 , 0
      10     .06       0   222.5    .045       0   237.5     .06       0
Bank Sta=222.5,237.5
XS Rating Curve= 0 ,0
Exp/Cntr=0.3,0.1

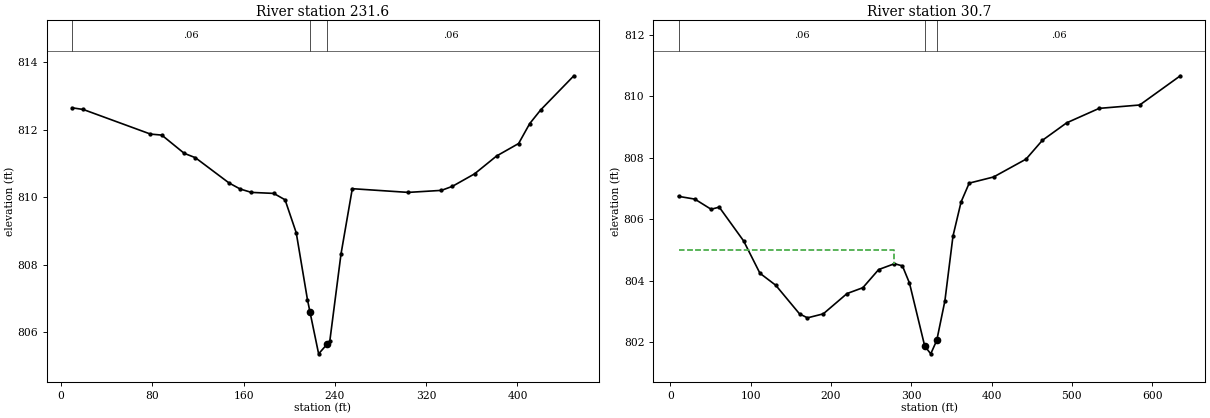
Type RM Length L Ch R = 1 ,231.6   ,201.9,200.9,187
XS GIS Cut Line= 3
     1640395.273      238233.947     1640680.681      238339.621
     1640808.012      238270.168
#Sta/Elev= 28
     9.8  812.65    19.6   812.6    78.5  811.87    88.4  811.84     108   811.3
   117.8  811.17   147.3  810.42   157.1  810.24   166.9  810.14   186.5  810.11
   196.4  809.92   206.2  808.94     216  806.96   218.3  806.58   225.8  805.35
   233.3  805.64   235.6  805.73   245.4  808.31   255.3  810.25   304.3  810.14
   333.4   810.2     343  810.32   362.4  810.69   381.7  811.22     401  811.59
   410.7  812.18   420.4  812.59   449.4   813.6
#Mann= 3 , 0 , 0
     9.8     .06       0   218.3    .045       0   233.3     .06       0
Bank Sta=218.3,233.3
XS Rating Curve= 0 ,0
Exp/Cntr=0.3,0.1

Type RM Length L Ch R = 1 ,30.7    ,29.8,30.7,44.6
XS GIS Cut Line= 5
     1640326.483      238296.613     1640343.538      238406.788
      1640500.81      238489.099     1640551.179      238505.316
     1640790.577      238335.946
#Sta/Elev= 30
    10.1  806.74    30.4  806.65    50.7  806.32    60.8  806.39    91.2  805.29
   111.5  804.24   131.2  803.85   160.8  802.92   170.7  802.79   190.4  802.92
     220  803.58   239.7  803.77   259.4  804.36   279.1  804.55     289  804.48
   297.8  803.92   316.8  801.87   324.3  801.62   331.8  802.06   341.9  803.34
     352  805.45   362.1  806.56   372.2  807.17   402.6  807.37     443  807.95
   463.3  808.56   493.6  809.13     534   809.6   584.6  809.71   635.2  810.66
#Mann= 3 , 0 , 0
    10.1     .06       0   316.8    .045       0   331.8     .06       0
#XS Ineff= 2 , 0
       0   279.1     805               0
Permanent Ineff=
       F       F
Bank Sta=316.8,331.8
XS Rating Curve= 0 ,0
Exp/Cntr=0.3,0.1

Chan Stop Cuts=-1
Use User Specified Reach Order=0